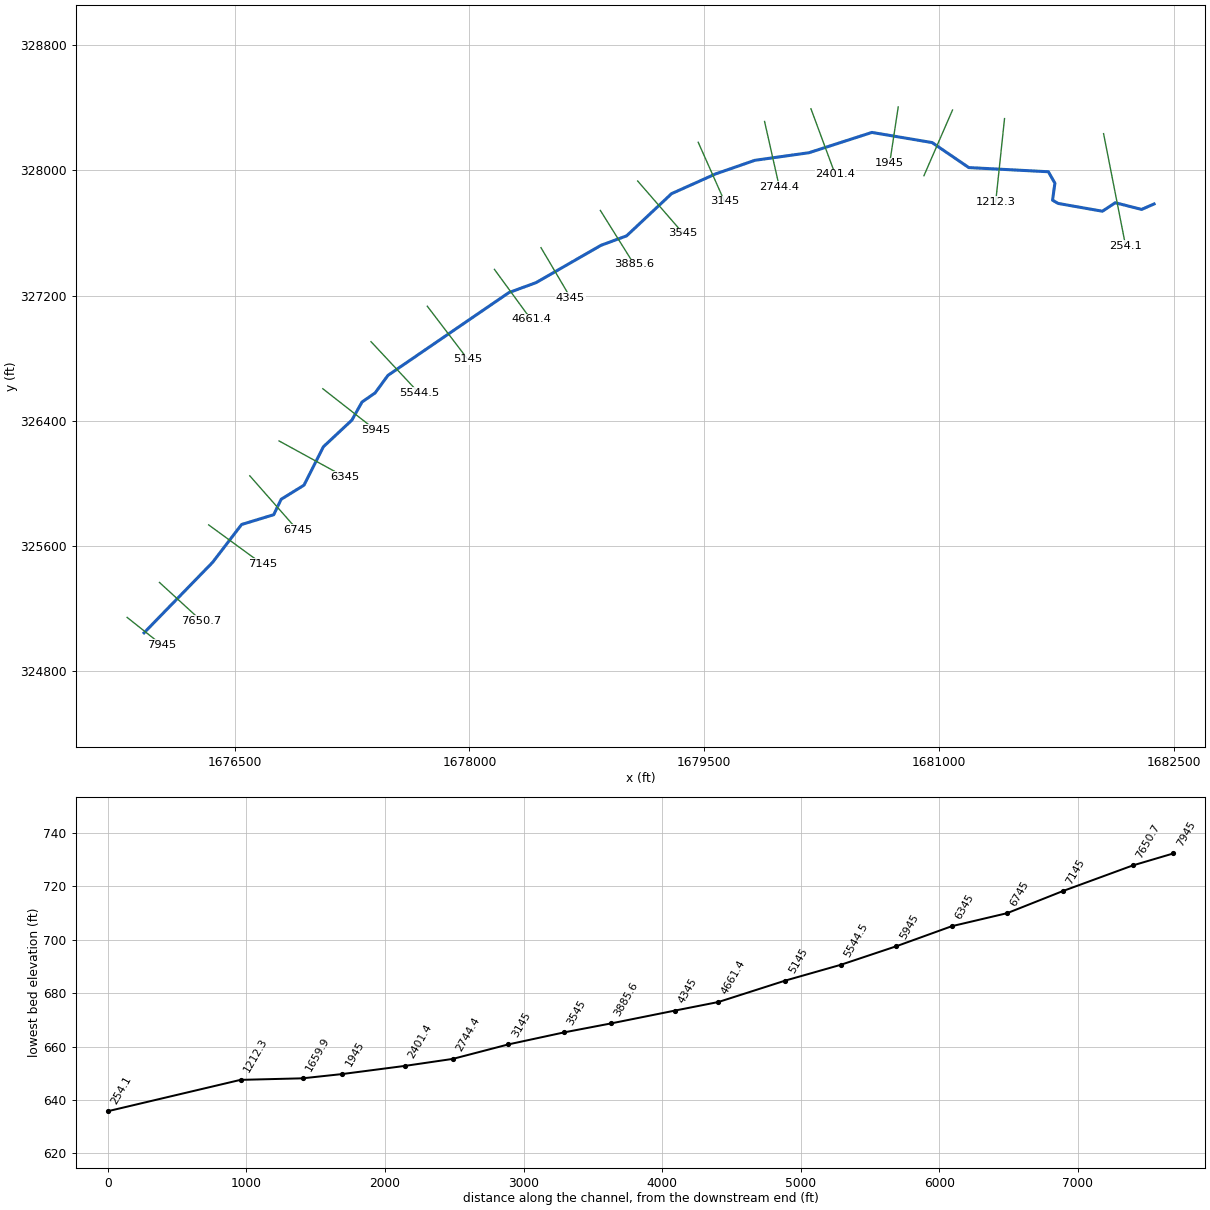
--- BUFFALOCRK.prj (project) ---

Proj Title=BUFFALOCRK
Current Plan=p01
Default Exp/Contr=0,0
English Units
Geom File=g01
Flow File=f01
Plan File=p01
BEGIN DESCRIPTION:
END DESCRIPTION:
DSS Export Rating Curves= 0
DSS Export Rating Curve Sorted= 0
DSS Export Volume Flow Curves= 0
DXF OffsetX= 0
DXF OffsetY= 0
DXF ScaleX= 0
DXF ScaleY= 0

--- BUFFALOCRK.p01 (plan) ---

Plan Title=Floodplain
Program Version=4.00
Geom File=g01
Flow File=f01
K Sum by GR=0
Std Step Tol=0.01
Critical Tol=0.01
Num of Std Step Trials=20
Max Error Tol=0.3
Flow Tol Ratio=0.001
Split Flow NTrial=30
Split Flow Tol=0.02
Split Flow Ratio=0.02
Log Output Level=0
Friction Slope Method=1
Unsteady Friction Slope Method=2
Unsteady Bridges Friction Slope Method=1
Global Log Level=0
CheckData=False
Run HTab=0
Run UNet=0
Run PostProcess=0
UNET Theta=0
UNET Theta Warmup=0
UNET ZTol=0
UNET ZSATol=0
UNET MxIter=0
UNET MaxInSteps=0
UNET DtIC=0
UNET DtMin=0
UNET MaxCRTS=0
UNET WFStab=0
UNET SFStab=0
UNET WFX=0
UNET SFX=0
UNET DSS MLevel=0
UNET DZMax Abort=0
UNET Convert EG Bridges=0
UNET Use Existing IB Tables=0
UNET Froude Limit=0
UNET Froude Power=0
Write IC File=0
Echo Input=False
Echo Output=False
Write Detailed=0

--- BUFFALOCRK.f01 (steady flow) ---

Flow Title=NFF Regression Equation
Program Version=4.00
Number of Profiles=1
Profile Names=P100yr
River Rch & RM=BUFFALOCRK,Main      ,7945
888.6882
River Rch & RM=BUFFALOCRK,Main      ,5145
941.8351
River Rch & RM=BUFFALOCRK,Main      ,4661.4
1362.415
River Rch & RM=BUFFALOCRK,Main      ,2744.4
1465.296
River Rch & RM=BUFFALOCRK,Main      ,254.1
1585.229
Boundary for River Rch & Prof#=BUFFALOCRK,Main      ,1
Up Type=0
Dn Type=3
Dn Slope=0.00635

--- BUFFALOCRK.g01 (geometry) ---

Geom Title=USGS 10m DEM
Program Version=4.10

River Reach=BUFFALOCRK      ,Main
Reach XY= 30
     1675921.616      325043.165      1676359.51      325493.801
     1676544.862      325735.917     1676749.908      325798.474
     1676797.404      325896.942     1676943.369      325987.301
     1677067.323      326232.892       1677249.2      326403.185
     1677314.073       326519.03     1677397.481      326576.952
     1677479.731      326689.322     1678252.417      327218.733
     1678426.185      327282.448      1678840.91      327521.089
     1679004.251      327581.328     1679291.547      327851.247
      1679573.05      327977.518     1679823.275      328064.402
     1680169.652      328113.057     1680571.634      328242.803
     1680956.448      328177.852     1681190.406       328018.02
     1681698.857      327991.381     1681740.552      327918.414
     1681725.495      327809.543     1681761.399      327788.696
     1682044.001      327738.893     1682126.233      327793.329
     1682294.173      327750.475     1682374.089      327785.221

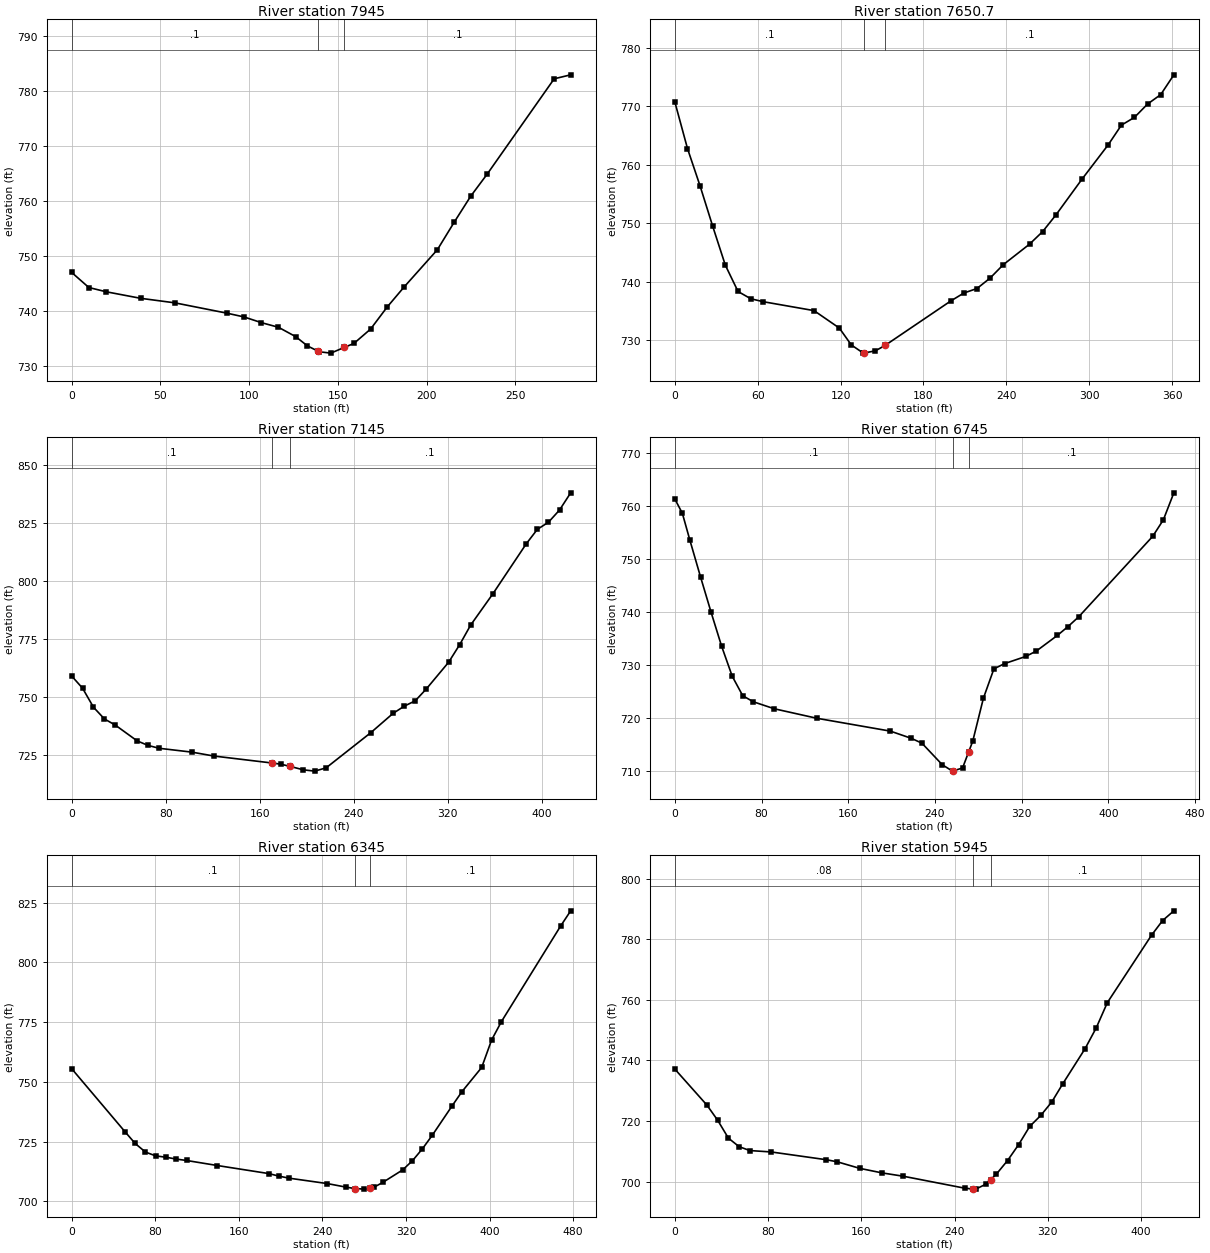
Type RM Length L Ch R = 1 ,7945    ,295.8,294.2,292.6
XS GIS Cut Line= 5
      1675813.53      325141.767     1675912.339      325063.301
     1675927.835      325050.996     1675930.686      325048.732
     1676033.695      324966.931
#Sta/Elev= 25
       0  747.02     9.7  744.27    19.4   743.5    38.8  742.31    58.2  741.48
    87.4  739.61    97.1  738.92   106.8  737.89   116.5  737.04   126.2  735.34
   132.8  733.66   138.5  732.74   139.4  732.59     146  732.34   153.5  733.37
     159   734.1   168.4  736.72   177.8  740.75   187.2  744.34     206  751.14
   215.4   756.1   224.8  760.88   234.2  764.95   271.8  782.22   281.1  782.94
#Mann= 3 , 0 , 0
       0      .1       0   138.5    .045       0   153.5      .1       0
Bank Sta=138.5,153.5
XS Rating Curve= 0 ,0
Exp/Cntr=0.3,0.1

Type RM Length L Ch R = 1 ,7650.7  ,503,505.5,508.1
XS GIS Cut Line= 4
     1676020.082        325365.3      1676107.88      325284.818
     1676146.359      325249.546     1676286.391      325121.183
#Sta/Elev= 30
       0  770.81     9.2   762.8    18.3  756.42    27.5  749.48    36.6  742.86
    45.8  738.36      55  737.12    64.1  736.61   100.8  735.09   119.1  732.11
   127.8  729.22   136.5  727.82   137.2  727.85   145.2  728.21   152.2  729.13
   199.8  736.74   209.3   738.1   218.8  738.87   228.3  740.66   237.8  742.94
   256.8  746.45   266.3   748.6   275.8  751.41   294.8  757.57   313.8  763.45
   323.3   766.8   332.8  768.14   342.3  770.42   351.8  772.03   361.3  775.41
#Mann= 3 , 0 , 0
       0      .1       0   137.2    .045       0   152.2      .1       0
Bank Sta=137.2,152.2
XS Rating Curve= 0 ,0
Exp/Cntr=0.3,0.1

Type RM Length L Ch R = 1 ,7145    ,405.2,400,394.9
XS GIS Cut Line= 4
     1676334.318      325733.282     1676454.618      325645.506
     1676517.102      325599.914     1676677.385      325482.965
#Sta/Elev= 30
       0  759.15     9.3  753.89    18.6   745.7    27.9  740.66    37.2     738
    55.8   731.2    65.2  729.24    74.5  728.03   102.4  726.37     121   724.7
   170.6  721.69   177.9   721.2   185.6  720.28   197.3  718.75   206.9   718.2
   216.6  719.62   254.6  734.75   273.5  743.03     283  746.14   292.4  748.46
   301.8  753.54   320.8  765.04   330.2  772.59   339.6  781.07   358.5  794.52
   386.9  816.03   396.3  822.23   405.8  825.32   415.2  830.56   424.7  837.96
#Mann= 3 , 0 , 0
       0      .1       0   170.6    .045       0   185.6      .1       0
Bank Sta=170.6,185.6
XS Rating Curve= 0 ,0
Exp/Cntr=0.3,0.1

Type RM Length L Ch R = 1 ,6745    ,391.4,399.9,408.5
XS GIS Cut Line= 5
     1676597.168      326047.093     1676606.446       326036.54
     1676747.737      325875.831     1676778.684      325840.631
     1676901.179      325701.301
#Sta/Elev= 30
       0  761.42       7  758.68      14  753.56    23.8  746.64    33.5  739.98
    43.2  733.57      53  727.89    62.7  724.21    72.4  723.07    91.9  721.74
   130.8  719.96   198.9  717.52   218.3  716.15     228  715.24   246.8  711.16
   256.2  709.96   265.5  710.56   271.2  713.64   274.9  715.64   284.7  723.74
   294.4  729.29   304.2  730.28   323.7  731.63   333.5  732.65     353  735.62
   362.8  737.29   372.6  739.12   440.9  754.34   450.7  757.45   460.4  762.56
#Mann= 3 , 0 , 0
       0      .1       0   256.2    .045       0   271.2      .1       0
Bank Sta=256.2,271.2
XS Rating Curve= 0 ,0
Exp/Cntr=0.3,0.1

Type RM Length L Ch R = 1 ,6345    ,403.7,400.2,396.7
XS GIS Cut Line= 5
     1676784.071      326270.232      1676828.77      326245.731
     1676975.489      326165.312      1677045.22       326127.09
     1677202.994      326040.612
#Sta/Elev= 30
       0   755.5      51  729.14    60.8  724.18    70.7  720.57    80.5  718.98
    90.3  718.42   100.2  717.64     110  717.06   139.6  714.94   188.8  711.57
   198.6  710.49   208.4  709.64   244.8  707.39   262.5  705.92   270.9  705.33
   280.1  705.07   285.9  705.52     289  705.76   297.8  707.87   316.8  713.09
   326.2  716.94   335.7   721.9   345.2   727.6   364.1  739.85   373.6  745.85
   392.5  755.98     402  767.48   411.4  775.18   468.3  815.33   477.7  821.53
#Mann= 3 , 0 , 0
       0      .1       0   270.9    .045       0   285.9      .1       0
Bank Sta=270.9,285.9
XS Rating Curve= 0 ,0
Exp/Cntr=0.3,0.1

Type RM Length L Ch R = 1 ,5945    ,403.5,400,396.5
XS GIS Cut Line= 5
     1677063.602      326603.958     1677143.211      326541.597
     1677211.024      326488.475     1677280.834       326433.79
     1677400.656      326339.928
#Sta/Elev= 30
       0  737.17    27.6  725.26    36.8  720.27      46  714.38    55.2  711.56
    64.4  710.28    82.7  709.82   129.8  707.27   139.4  706.57   158.6  704.42
   177.7  702.92   196.1  701.81   249.3  697.83   256.1  697.62   258.2  697.56
   267.1  699.22   271.1  700.71     276  702.54   285.5  706.98     295  712.22
   304.5  718.23     314  721.85   323.5  726.33     333  732.37     352  743.86
   361.6  750.74   371.1  759.04   409.1  781.33   418.6  786.15   428.2  789.34
#Mann= 3 , 0 , 0
       0     .08       0   256.1    .045       0   271.1      .1       0
Bank Sta=256.1,271.1
XS Rating Curve= 0 ,0
Exp/Cntr=0.3,0.1

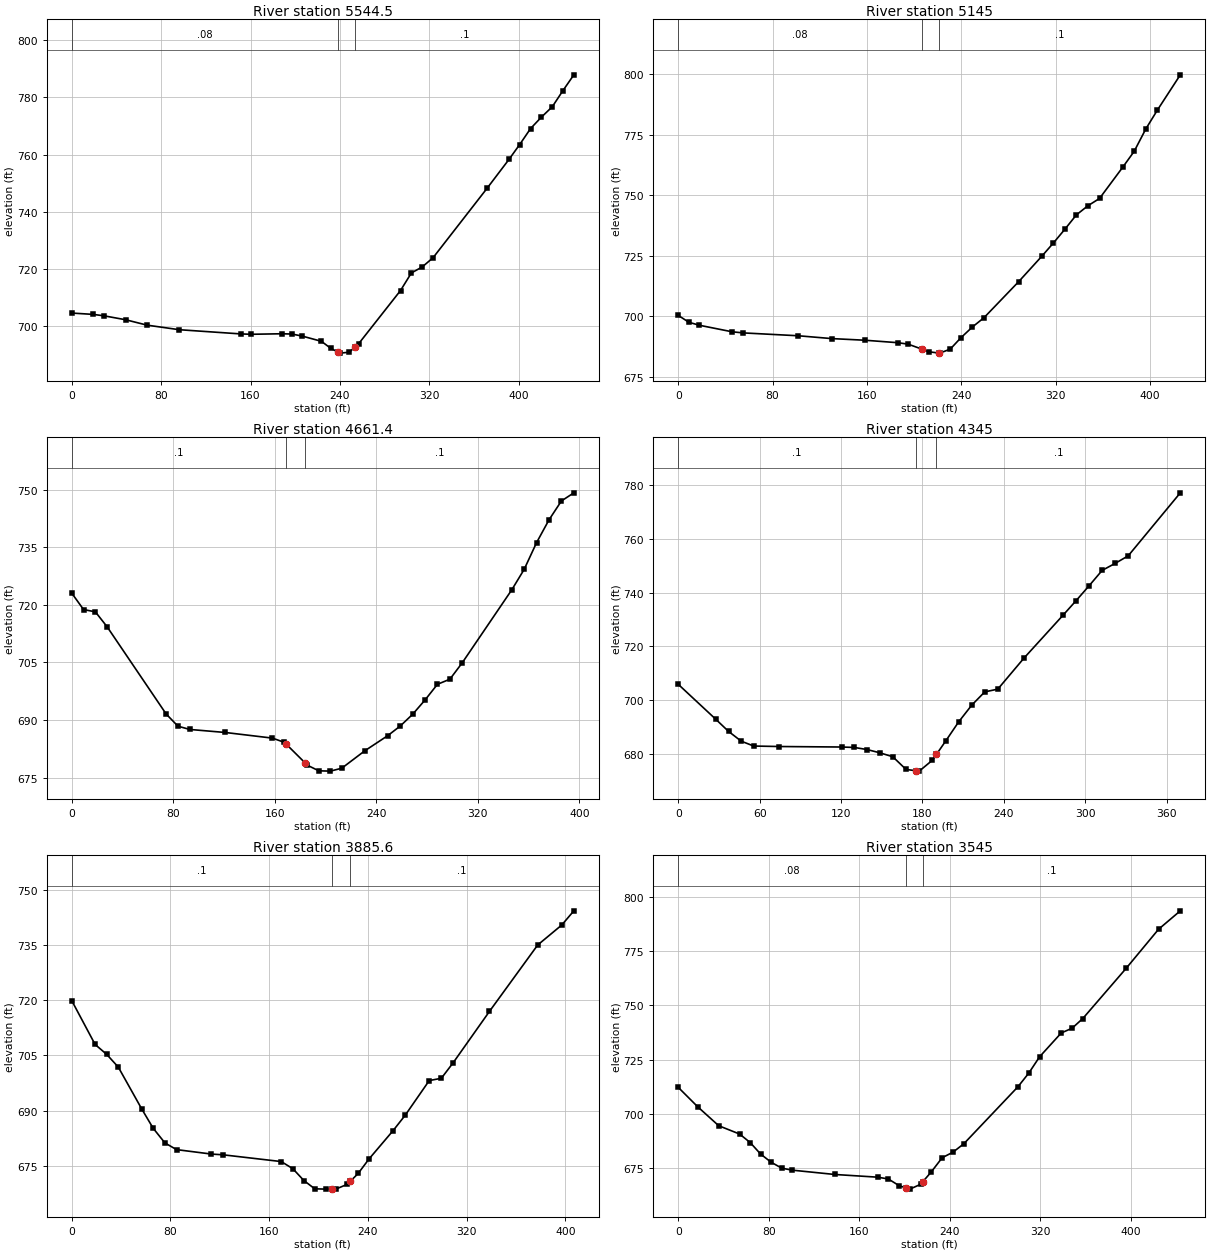
Type RM Length L Ch R = 1 ,5544.5  ,401.9,399.6,397.3
XS GIS Cut Line= 5
     1677371.497       326904.91     1677443.839      326827.433
       1677518.3      326747.686     1677552.402      326711.163
      1677678.16      326576.478
#Sta/Elev= 30
       0  704.63    19.3  704.16    28.9  703.66    48.2  702.29    67.4   700.4
    96.4   698.8   151.5  697.33   160.6  697.21   187.8  697.39   196.9   697.3
     206   696.6   223.4  694.75   231.8  692.29   238.3  690.98   240.1  690.62
   248.4  690.94   253.3   692.7   256.8  693.95   294.2  712.51   303.9  718.65
   313.6  720.75   323.3  723.97   371.8  748.33   391.2  758.32   400.8  763.53
   410.6  769.15   420.2   773.1     430  776.76   439.6  782.44   449.3  787.92
#Mann= 3 , 0 , 0
       0     .08       0   238.3    .045       0   253.3      .1       0
Bank Sta=238.3,253.3
XS Rating Curve= 0 ,0
Exp/Cntr=0.3,0.1

Type RM Length L Ch R = 1 ,5145    ,484,483.6,483.1
XS GIS Cut Line= 5
     1677731.128      327131.526     1677747.433      327110.126
     1677838.338      326990.812     1677876.328      326940.951
     1677989.091      326792.949
#Sta/Elev= 30
       0  700.32       9  697.47    17.9  696.24    45.6  693.54      55  693.08
   101.9  691.89     130  690.73   158.2  690.05   185.9  689.04   194.8  688.44
   206.4   686.4   212.7  685.25   221.4  684.74   221.7  684.72   230.6  686.39
   239.6  691.07   249.4  695.54   259.2  699.36   288.6  714.26   308.1   724.7
   317.9  730.16   327.7  735.88   337.5  741.84   347.3  745.62   357.1  748.62
   376.7  761.47   386.5   768.1   396.3   777.3   406.1  785.09   425.6  799.71
#Mann= 3 , 0 , 0
       0     .08       0   206.4    .045       0   221.4      .1       0
Bank Sta=206.4,221.4
XS Rating Curve= 0 ,0
Exp/Cntr=0.3,0.1

Type RM Length L Ch R = 1 ,4661.4  ,318.7,316.3,313.9
XS GIS Cut Line= 4
     1678159.866      327367.153     1678258.609      327231.871
     1678306.725       327165.95     1678393.129      327047.572
#Sta/Elev= 30
       0  723.05     9.3  718.78    18.6  718.19    27.9  714.27    74.4  691.56
    83.7  688.39      93  687.54     121  686.75   158.2  685.28   167.5  684.18
   168.6  683.84   183.6  678.92   185.6  678.23   194.7  676.76   203.8  676.68
   212.8  677.44     231  681.99   249.1  685.94   258.9  688.44   268.6  691.47
   278.4  695.21   288.2  699.31     298  700.63   307.7  704.89   346.8  723.93
   356.6  729.29   366.3  736.21   376.1  742.15   385.9  747.08   395.7   749.2
#Mann= 3 , 0 , 0
       0      .1       0   168.6    .045       0   183.6      .1       0
Bank Sta=168.6,183.6
XS Rating Curve= 0 ,0
Exp/Cntr=0.3,0.1

Type RM Length L Ch R = 1 ,4345    ,458.8,459.4,460
XS GIS Cut Line= 4
     1678457.558      327505.804     1678532.884      327377.978
     1678557.617      327336.007     1678645.426      327186.999
#Sta/Elev= 29
       0  705.82    27.8  692.72    37.1  688.25    46.4  684.62    55.6   682.8
    74.2  682.62   120.6  682.43   129.8  682.27   139.1  681.49   148.4   680.3
   158.1  678.81   167.9  674.06   175.3  673.59   177.6  673.44   187.3  677.51
   190.3   679.7   197.1  684.67   206.7  691.84   216.3  698.05   225.9     703
   235.5  704.02   254.7  715.54   283.6  731.61   293.2  737.02   302.8  742.59
   312.4  748.31     322  750.93   331.6  753.74     370  777.24
#Mann= 3 , 0 , 0
       0      .1       0   175.3    .045       0   190.3      .1       0
Bank Sta=175.3,190.3
XS Rating Curve= 0 ,0
Exp/Cntr=0.3,0.1

Type RM Length L Ch R = 1 ,3885.6  ,337,340.6,344.2
XS GIS Cut Line= 4
     1678836.756      327743.949     1678931.763      327591.954
     1678964.453      327539.656     1679052.412      327398.935
#Sta/Elev= 30
       0  719.88    18.9  707.98    28.3  705.28    37.7  701.82    56.6   690.5
      66  685.18    75.5  681.21    84.9  679.39   113.2  678.18   122.6  677.98
   169.8  676.14   179.2  674.19   188.1  670.99   196.9  668.74   205.7  668.65
   210.7   668.7   214.5  668.73   223.3  669.96   225.7  670.76   232.1  672.91
   240.9  676.85   260.4  684.55   270.2  688.72   289.7  698.16   299.5  698.78
   309.2  703.05   338.5  716.96   377.6  735.01   397.1  740.44   406.9   744.3
#Mann= 3 , 0 , 0
       0      .1       0   210.7    .045       0   225.7      .1       0
Bank Sta=210.7,225.7
XS Rating Curve= 0 ,0
Exp/Cntr=0.3,0.1

Type RM Length L Ch R = 1 ,3545    ,406.6,399.9,393.1
XS GIS Cut Line= 5
     1679075.212      327932.028      1679080.38      327926.074
     1679153.446       327841.89     1679221.937      327762.979
     1679366.229      327596.732
#Sta/Elev= 30
       0  712.21    17.2  703.26    35.8  694.51    54.3  690.67    63.6  686.76
    72.9  681.42    82.2  677.66    91.5  674.95   100.8  674.02   138.4  672.03
   176.4  670.78   185.8  669.95   195.4  666.85   201.4  665.84   204.8  665.27
   214.3  667.48   216.4  668.75   223.8  673.23   233.4  679.75     243  682.32
   252.6  686.21   300.4  712.47     310  718.78   319.6  726.33   338.7  737.29
   348.3  739.48   357.8  743.96   396.1   767.1   424.8  785.14     444  793.62
#Mann= 3 , 0 , 0
       0     .08       0   201.4    .045       0   216.4      .1       0
Bank Sta=201.4,216.4
XS Rating Curve= 0 ,0
Exp/Cntr=0.3,0.1

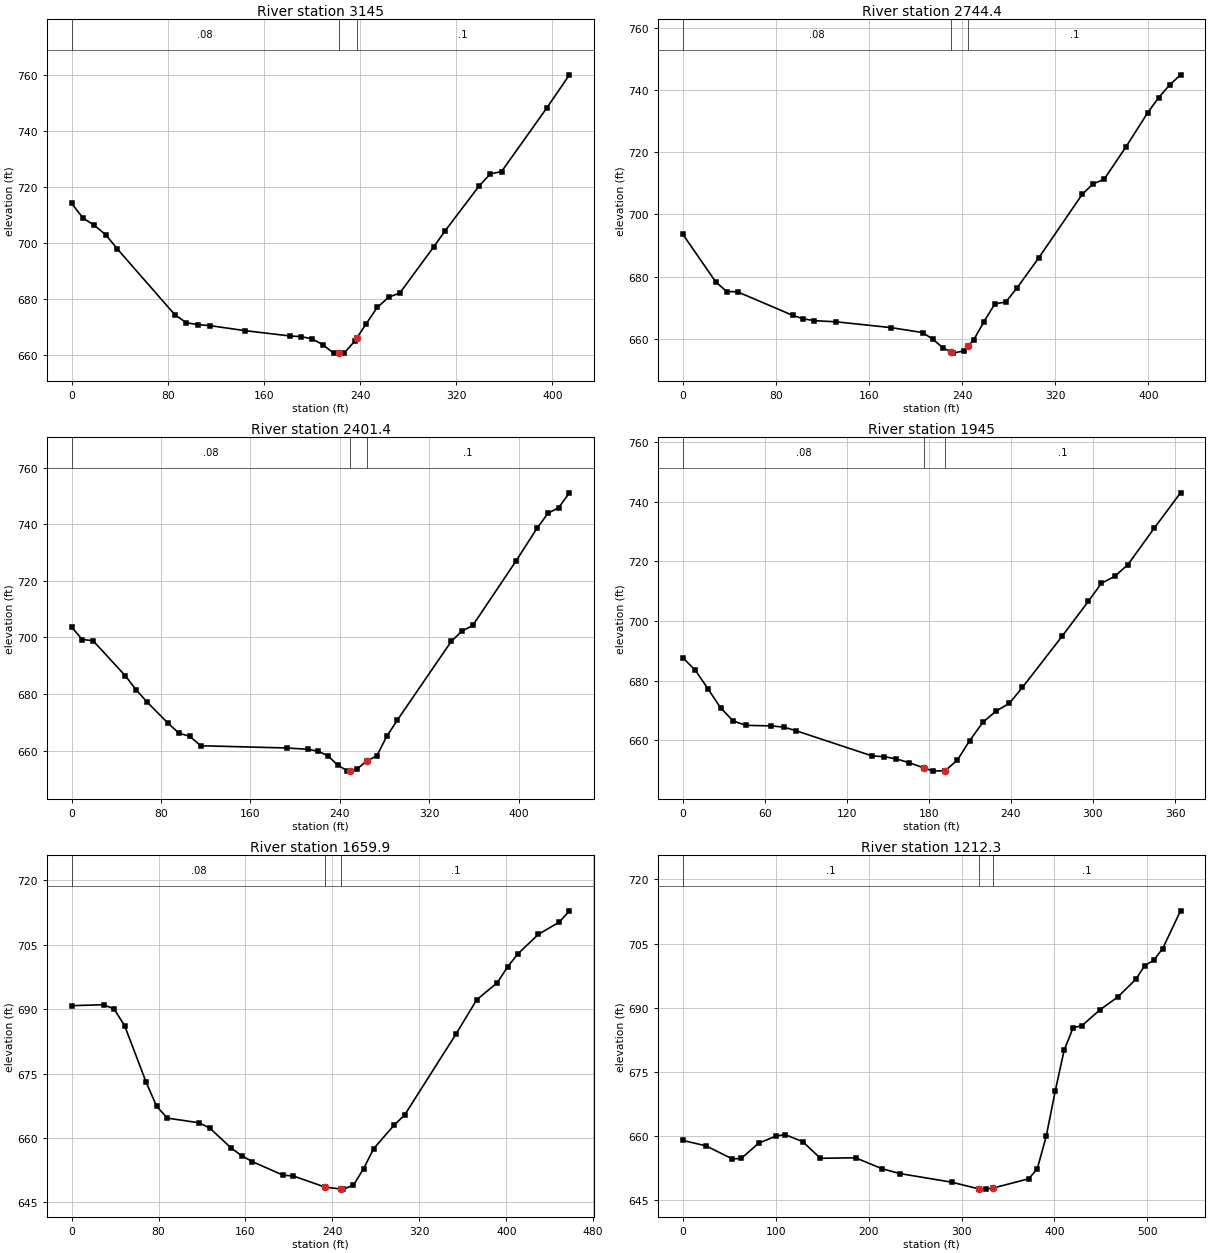
Type RM Length L Ch R = 1 ,3145    ,404.8,400.4,395.9
XS GIS Cut Line= 5
     1679461.877      328179.807     1679488.844       328119.13
     1679532.155      328021.678     1679561.337      327956.019
     1679630.078       327801.35
#Sta/Elev= 30
       0  714.27     9.5     709      19  706.39    28.5  703.01    37.9  698.06
    85.8  674.55    95.5  671.63   105.2  670.95   114.9  670.62     144  668.83
     182   666.9     191  666.68     200  665.89     209  663.81     218  660.79
   222.5  660.82   226.9  660.84   235.9  665.24   237.5  666.29   244.9  671.15
   254.3  677.08   263.7  680.72   273.1  682.26   301.3  698.71   310.7  704.39
   338.9  720.36   348.3  724.73   357.7  725.59   395.4  748.32   414.2  760.11
#Mann= 3 , 0 , 0
       0     .08       0   222.5    .045       0   237.5      .1       0
Bank Sta=222.5,237.5
XS Rating Curve= 0 ,0
Exp/Cntr=0.3,0.1

Type RM Length L Ch R = 1 ,2744.4  ,340.2,343.2,346.2
XS GIS Cut Line= 4
     1679885.771       328312.82     1679927.248      328128.692
     1679942.646      328060.333     1679979.752      327895.611
#Sta/Elev= 30
       0   693.7    28.3  678.35    37.8  675.19    47.2  675.09    94.4  667.54
   103.8  666.39   113.2  665.81   132.1  665.44   179.3  663.56   206.3  661.97
     215   659.8   223.8  657.05   230.4  655.78   232.5  655.37   241.3  656.08
   245.4  657.74     250   659.6   258.8  665.47   268.2   671.2   277.6  671.82
     287  676.21   305.7  685.91   343.2  706.42   352.6  709.83     362  711.28
   380.8  721.68   399.5  732.72   408.9  737.56   418.3  741.62   427.7   744.9
#Mann= 3 , 0 , 0
       0     .08       0   230.4    .045       0   245.4      .1       0
Bank Sta=230.4,245.4
XS Rating Curve= 0 ,0
Exp/Cntr=0.3,0.1

Type RM Length L Ch R = 1 ,2401.4  ,467.8,456.4,445
XS GIS Cut Line= 4
     1680182.126      328394.013     1680255.407       328195.65
     1680279.777      328129.685     1680336.418      327976.366
#Sta/Elev= 30
       0  703.66     9.6  699.27    19.2  698.86    48.1  686.43    57.7  681.53
    67.3  677.27    86.5   669.6    96.1  666.14   105.7  665.07   115.4  661.73
   192.2  660.94   211.5  660.47   220.3  659.81     229  658.22   237.8  654.99
   246.6  652.76   248.8  652.96   255.4  653.56   263.8  656.29     273  658.18
   281.8  665.04   291.4  670.84   339.5  698.59   349.1  702.24   358.7  704.23
   397.2  726.87   416.4  738.69     426  743.86   435.6  745.89   445.2   751.1
#Mann= 3 , 0 , 0
       0     .08       0   248.8    .045       0   263.8      .1       0
Bank Sta=248.8,263.8
XS Rating Curve= 0 ,0
Exp/Cntr=0.3,0.1

Type RM Length L Ch R = 1 ,1945    ,290.9,285,279.2
XS GIS Cut Line= 4
     1680739.537      328405.646     1680718.788      328268.707
     1680708.099       328198.16     1680685.007      328045.755
#Sta/Elev= 30
       0  687.74     9.2  683.55    18.5   677.3    27.7  670.91    36.9  666.52
    46.2  665.02    64.6  664.84    73.9  664.44    83.1  663.19   138.5  654.78
   147.4  654.52   156.3  653.76   165.3  652.56   176.7  650.69   183.1  649.68
   191.7  649.85     192  649.86   200.9  653.39   209.8  659.86   219.5  666.05
   229.1   669.8   238.8  672.38   248.4  677.72   277.3  694.82   296.6  706.59
   306.2  712.66   315.8  714.94   325.5  718.88   344.7  731.07     364  742.96
#Mann= 3 , 0 , 0
       0     .08       0   176.7    .045       0   191.7      .1       0
Bank Sta=176.7,191.7
XS Rating Curve= 0 ,0
Exp/Cntr=0.3,0.1

Type RM Length L Ch R = 1 ,1659.9  ,440.4,447.5,454.6
XS GIS Cut Line= 4
     1681086.452      328386.036     1681016.229      328224.495
     1680975.641      328131.127     1680903.823      327965.917
#Sta/Elev= 30
       0  690.83    29.4  691.05    39.1  690.08    48.9  686.12    68.5  673.08
    78.3  667.38    88.1  664.64   117.4  663.54   127.2   662.3   146.8  657.68
   156.6  655.85   166.4   654.5   194.6  651.33   203.9  651.16   233.3  648.56
   248.3   648.1   250.2  648.09   259.4  649.03   268.7  652.87     278  657.53
   296.9  663.04   306.4  665.34   353.8  684.26   372.8  692.22   391.7  696.17
   401.2  699.88   410.7  702.92   429.6  707.47   448.6  710.27   458.1  712.93
#Mann= 3 , 0 , 0
       0     .08       0   233.3    .045       0   248.3      .1       0
Bank Sta=233.3,248.3
XS Rating Curve= 0 ,0
Exp/Cntr=0.3,0.1

Type RM Length L Ch R = 1 ,1212.3  ,950.1,957.9,965.7
XS GIS Cut Line= 5
     1681418.787      328331.256      1681418.14      328325.145
     1681392.206      328080.241     1681378.614      327951.891
     1681362.381      327798.605
#Sta/Elev= 30
       0  658.92    25.1  657.64    53.5  654.58      63  654.69    81.9  658.28
   100.9  659.96   110.3  660.28   129.3   658.6   148.2  654.73   186.1  654.84
   214.5  652.28   233.5  651.16   289.3  649.14   319.3  647.53   326.2  647.51
   334.3  647.78   372.3  649.93   381.5  652.26   391.1  659.86   400.8  670.45
   410.4  680.01     420  685.26   429.7   685.8   448.9  689.47   468.2   692.5
   487.5  696.62   497.1  699.83   506.7  701.06   516.4  703.82   535.6  712.65
#Mann= 3 , 0 , 0
       0      .1       0   319.3    .045       0   334.3      .1       0
Bank Sta=319.3,334.3
XS Rating Curve= 0 ,0
Exp/Cntr=0.3,0.1

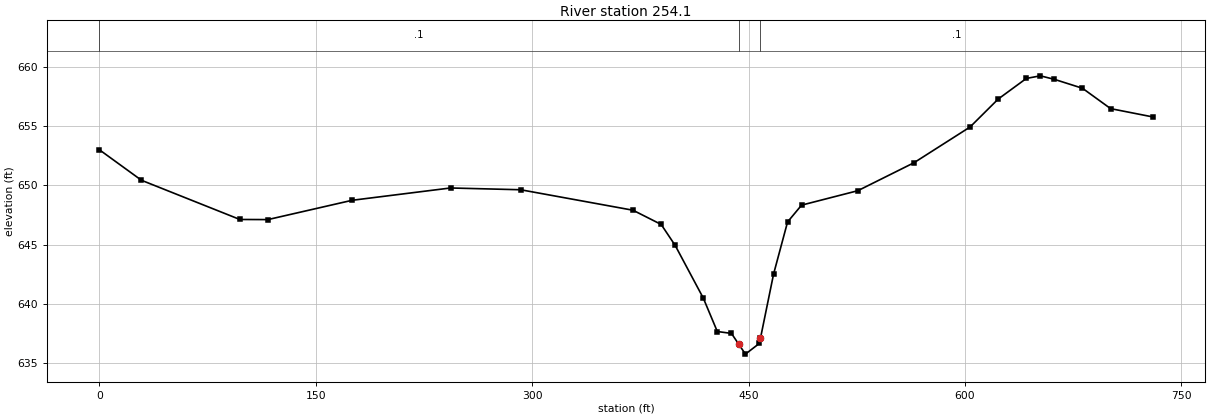
Type RM Length L Ch R = 1 ,254.1   ,239.4,254.1,268.7
XS GIS Cut Line= 2
     1682051.532      328234.992     1682192.136      327518.564
#Sta/Elev= 30
       0  653.02    29.2  650.44    97.4  647.13   116.8  647.12   175.2  648.75
   243.4  649.79     292  649.64   369.9  647.91   389.4  646.71   399.1  644.94
   418.6  640.49   428.3  637.67   438.1  637.51   443.2  636.59   447.8  635.76
   457.5  636.67   458.2  637.09   467.3  642.52     477  646.92   486.7  648.34
   525.7  649.56   564.6  651.92   603.5  654.94     623   657.3   642.5  659.04
   652.2  659.26     662  658.96   681.4  658.21   700.9  656.49   730.1  655.79
#Mann= 3 , 0 , 0
       0      .1       0   443.2    .045       0   458.2      .1       0
Bank Sta=443.2,458.2
XS Rating Curve= 0 ,0
Exp/Cntr=0.3,0.1

Chan Stop Cuts=-1
Use User Specified Reach Order=0
Composite Channel Slope=5